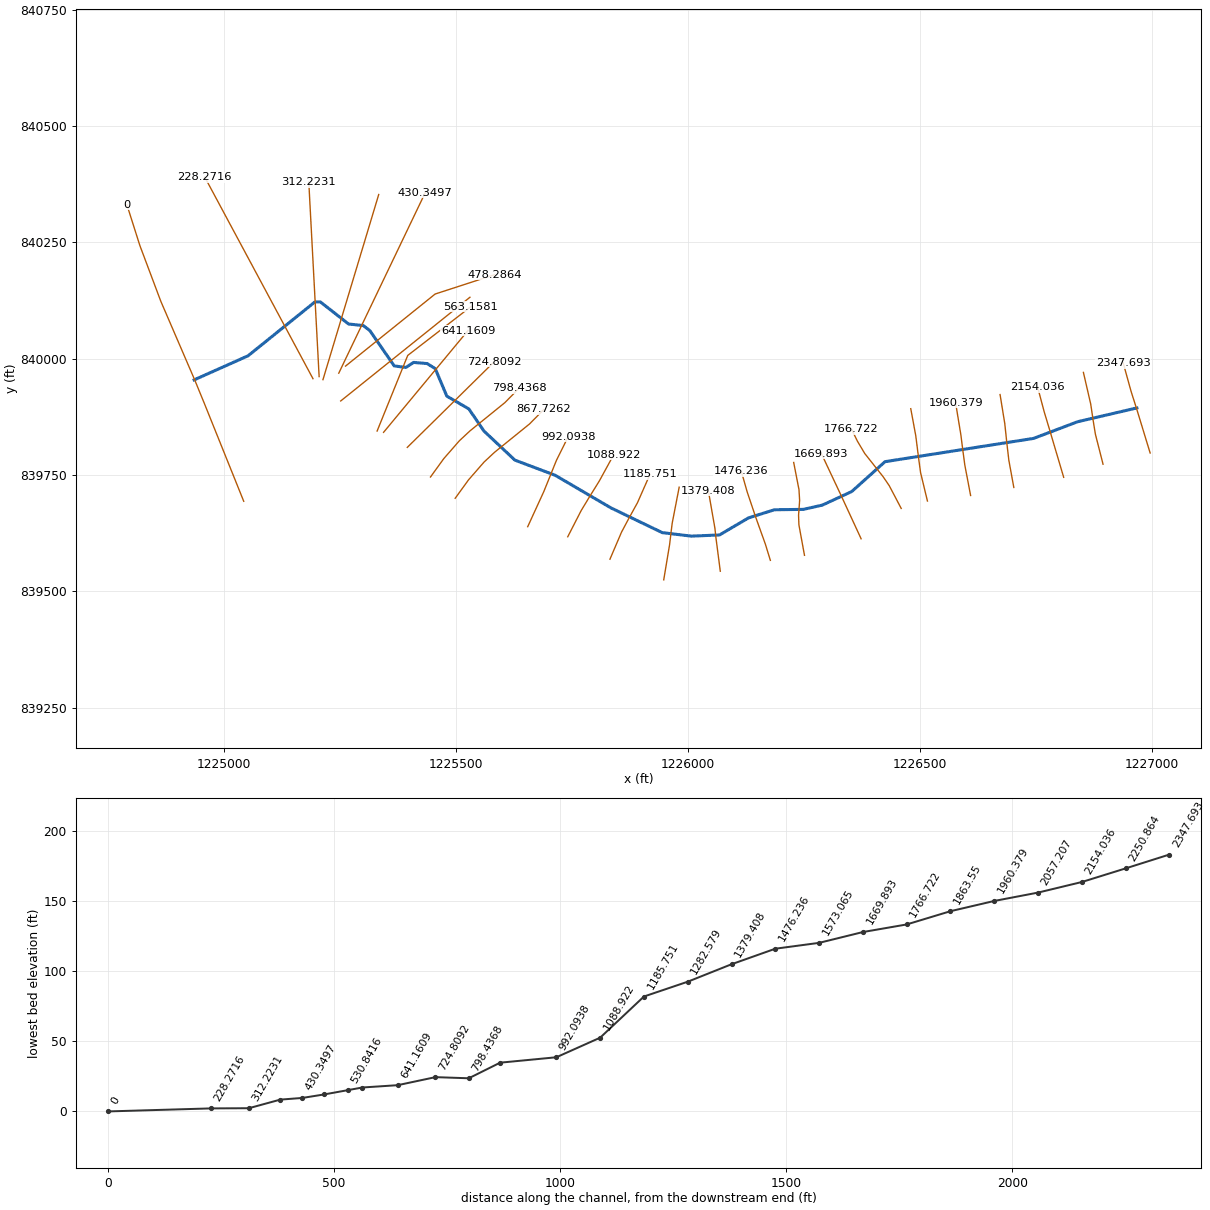
--- 38_ras.prj (project) ---

Proj Title=38
Current Plan=p01
Default Exp/Contr=0.3,0.1
English Units
Geom File=g01
Flow File=f01
Plan File=p01
Y Axis Title=Elevation
X Axis Title(PF)=Main Channel Distance
X Axis Title(XS)=Station
BEGIN DESCRIPTION:
RFD model 38 exported to HEC-RAS
END DESCRIPTION:

--- 38_ras.p01 (plan) ---

Plan Title=Plan 01
Program Version=4.10
Short Identifier=Plan 01
Geom File=g01
Flow File=f01
Subcritical Flow
Calc Critical at every XS
Secant Critical Depth

--- 38_ras.f01 (steady flow) ---

Flow Title=Flow 01
Program Version=5.01
Number of Profiles= 5
Profile Names=10yr,25yr,50yr,100yr,500yr
River Rch & RM=38,27,2347.693
  298.96  542.11  785.58 1086.45 2032.67
River Rch & RM=38,27,2250.864
  304.41  552.22  800.54 1107.58 2074.49
River Rch & RM=38,27,2057.207
  309.86  562.33   815.5 1128.73 2116.38
River Rch & RM=38,27,1960.379
  316.52  574.68  833.78  1154.6 2167.68
River Rch & RM=38,27, 1863.55
  320.15  581.42  843.76 1168.71  2195.7
River Rch & RM=38,27,1669.893
  324.39  589.28   855.4 1185.19 2228.44
River Rch & RM=38,27,1573.065
  332.24  603.87  877.02 1215.81 2289.34
River Rch & RM=38,27,1476.236
  335.27  609.48  885.34  1227.6  2312.8
River Rch & RM=38,27,1379.408
  338.29  615.09  893.66 1239.38 2336.28
River Rch & RM=38,27,1282.579
  343.72  625.19  908.64 1260.61  2378.6
River Rch & RM=38,27,1185.751
  346.14  629.68   915.3 1270.05 2397.43
River Rch & RM=38,27,1088.922
  349.15  635.29  923.62 1281.85 2420.98
River Rch & RM=38,27,992.0938
  350.96  638.66  928.62 1288.93 2435.12
River Rch & RM=38,27,867.7262
  353.98  644.27  936.94 1300.74 2458.71
River Rch & RM=38,27,798.4368
   358.2  652.12   948.6 1317.28 2491.76
River Rch & RM=38,27,641.1609
  364.23  663.34  965.26 1340.92 2539.04
River Rch & RM=38,27,563.1581
  367.85  670.07  975.25  1355.1 2567.45
River Rch & RM=38,27,478.2864
  373.27  680.16  990.25  1376.4 2610.11
River Rch & RM=38,27,312.2231
  561.75 1032.84 1516.67 2127.71  4136.3
River Rch & RM=38,27,228.2716
  566.51 1041.79 1530.08 2146.93 4175.79
River Rch & RM=38,27,       0
  573.06 1054.08 1548.51 2173.36 4230.15
Boundary for River Rch & Prof#=38,27,1
Up Type= 0
Dn Type= 2
Boundary for River Rch & Prof#=38,27,2
Up Type= 0
Dn Type= 2
Boundary for River Rch & Prof#=38,27,2
Up Type= 0
Dn Type= 2
Boundary for River Rch & Prof#=38,27,2
Up Type= 0
Dn Type= 2
Boundary for River Rch & Prof#=38,27,2
Up Type= 0
Dn Type= 2

--- 38_ras.g01 (geometry) ---

Geom Title=38
Program Version=4.10

River Reach=38,27
Reach XY= 30
1226967.62714792839893.8926742281226840.04573519839864.259208624
1226745.04576205839828.4258886161226425.04585455839778.425912743
1226353.37920706839714.2592671241226290.04589148839685.092610934
1226249.21256987839675.925948168 1226186.7125882839675.092616911
1226130.87927075839657.5926236971226068.37928804839620.925969672
1226007.54597249839618.4259722031225945.04599106839625.925971804
1225834.21269184839679.2592926091225714.21272912839749.259275427
1225627.54608886839781.7592683351225560.87944358839844.259251822
1225528.37945452839891.7592387371225480.87946927839919.259232014
1225455.87947834839978.425881924 1225438.3794838839989.259212565
1225409.21282577839991.7592126641225392.54616368839980.925883027
1225367.54617111839984.2592160931225315.04618875840060.092528563
1225300.87952656 840070.925859131225269.21286928840074.259192363
1225208.37955521840121.7591800871225196.71289197840121.759180477
1225052.54626426840005.9258855521224936.50170508839954.230032202

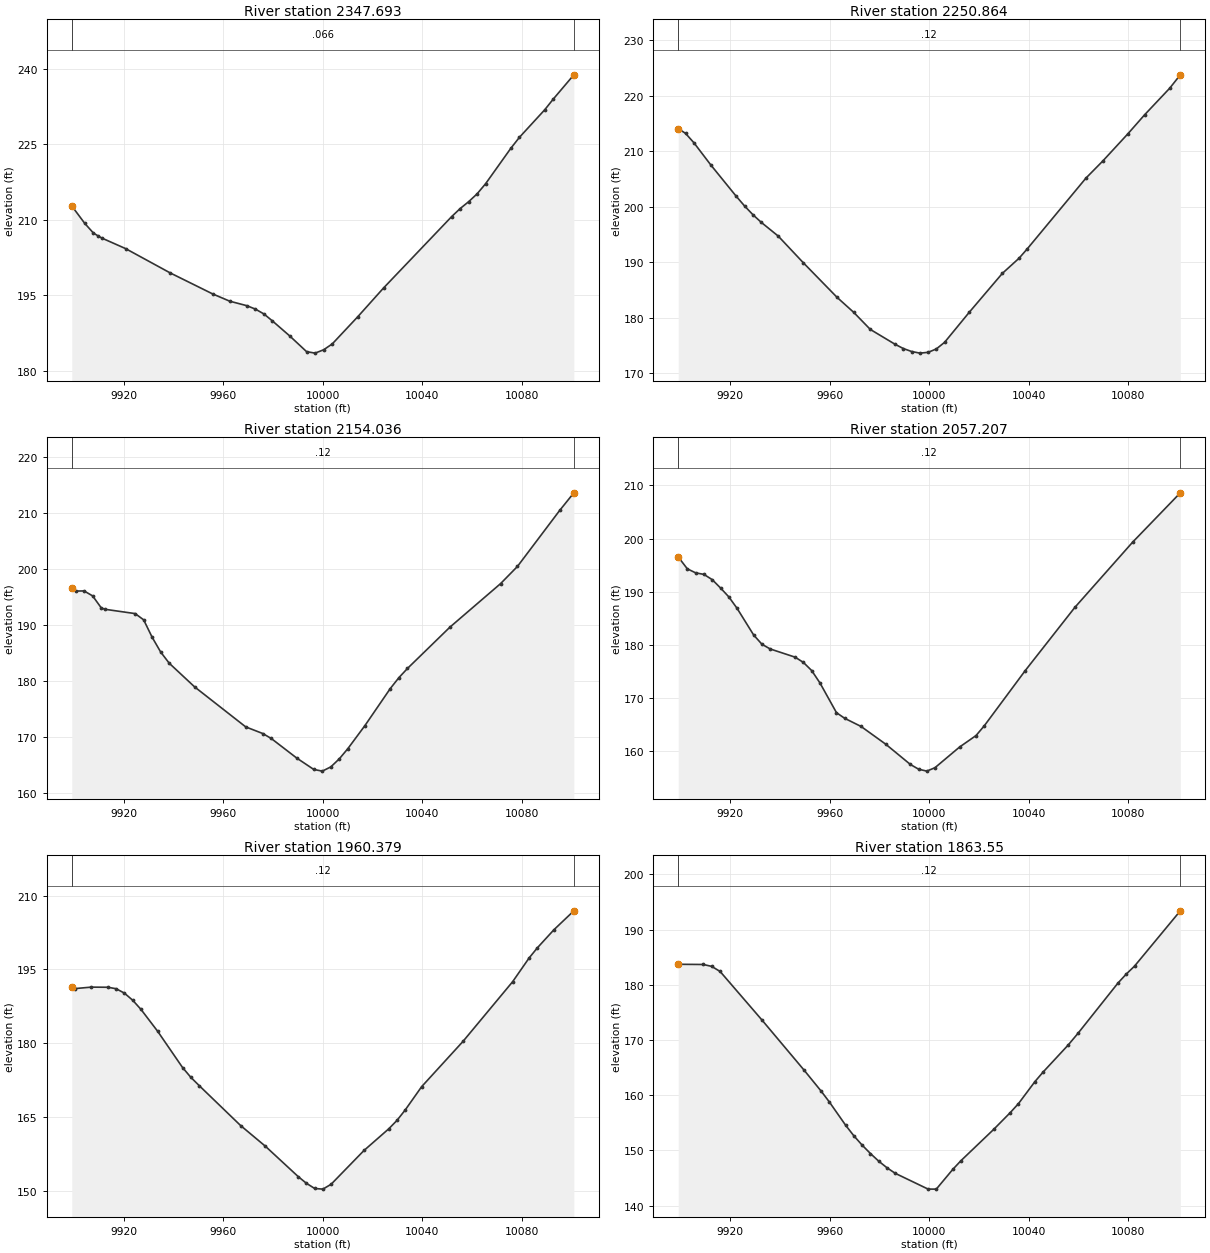
Type RM Length L Ch R = 1 ,2347.693,96.828500,96.828500,96.828500
XS GIS Cut Line= 5
1226996.29657201839797.0229339621226967.00020556839892.625021561
1226966.35949525839894.5196165821226955.17528694839929.621235243
1226938.24513517839990.464563196
#Sta/Elev= 30
 9899.01212.71449904.258209.23779907.689207.34869909.443206.80789911.121206.3305
9920.641 204.2489938.572199.42069955.729195.23059962.592193.78879969.455192.8995
9972.886 192.2239976.318191.25859979.749189.86719986.612186.92749993.475183.7707
9996.906183.476710000.35184.1447 10003.8185.301210014.13190.738710024.46196.4265
10051.85210.600610055.25212.190710058.66213.552310062.06215.108110065.47217.1133
10075.69224.197510079.09226.336810089.31231.833910092.71233.9392   10101238.7631
#Mann= 3 , 0 , 0
 9899.01   0.066       0 9899.01   0.066       0   10101   0.066       0
#XS Ineff= 2 , 0
       0                               0
Bank Sta=9899.01,10101
Exp/Cntr=0.3,0.1

Type RM Length L Ch R = 1 ,2250.864,96.828500,96.828500,96.828500
XS GIS Cut Line= 6
1226894.79490704839772.9341673481226878.34435301 839837.36738678
1226872.91588405839870.3958245371226872.74009649839872.388084242
1226868.17917579839902.4786228171226852.50265844839970.234562455
#Sta/Elev= 30
9899.028214.0848 9901.98213.21969905.366211.51019912.138207.52099922.297201.9054
9925.683200.13699929.069198.54759932.455197.15769939.227194.69899949.385189.8559
9962.929183.63159969.626 180.9249976.276177.8514 9986.25175.16919989.575174.3996
  9992.9173.86489996.225173.57219999.545173.715610002.85174.329810006.17175.5235
10016.13180.9673 10029.4187.9608 10036.1190.687310039.47 192.41310063.04205.1609
10069.78208.228110079.88213.137710086.62216.575110096.72221.374310100.98223.7874
#Mann= 3 , 0 , 0
9899.028    0.12       09899.028    0.12       010100.98    0.12       0
#XS Ineff= 2 , 0
       0                               0
Bank Sta=9899.028,10100.98
Exp/Cntr=0.3,0.1

Type RM Length L Ch R = 1 ,2154.036,96.828500,96.828500,96.828500
XS GIS Cut Line= 5
1226810.00061351839744.7938377011226781.51952547839840.644428435
 1226780.9766052839842.5693278021226768.09814292839885.246793911
1226753.82181455839938.792915981
#Sta/Elev= 30
9899.007196.50729900.544196.00489903.967196.02429907.389195.14049910.812193.0342
9912.238192.75489924.502191.97729927.925190.86079931.347187.7451 9934.77185.1157
9938.193183.1208 9948.46178.87039968.996171.73289975.841 170.5529979.264169.6637
9989.532  166.169996.377164.12939999.796 163.83310003.22164.589410006.64166.0314
10010.07 167.84710016.92171.955110027.14178.583810030.63180.544510034.06 182.178
10051.14189.556610071.52197.332810078.31200.405210095.28210.401310100.99213.5524
#Mann= 3 , 0 , 0
9899.007    0.12       09899.007    0.12       010100.99    0.12       0
#XS Ineff= 2 , 0
       0                               0
Bank Sta=9899.007,10100.99
Exp/Cntr=0.3,0.1

Type RM Length L Ch R = 1 ,2057.207,96.828500,96.828500,96.828500
XS GIS Cut Line= 6
1226702.54476352839722.981973042  1226691.828147839781.474548543
1226687.13026194839821.7199428581226686.95945971839823.712636161
1226683.06149885839860.3442982281226672.92661294839922.677342362
#Sta/Elev= 30
9899.015196.53069902.675 194.298 9906.01193.54519909.346193.25369912.681192.2676
9916.017190.70579919.352189.03269922.687186.87289929.358181.85929932.694180.1192
9936.029179.23099946.036177.69459949.371176.70329952.706175.17349956.042172.8341
9962.672167.25969965.975166.19939972.581164.6636 9982.49161.3322  9992.4157.5247
9995.703156.63699999.006156.2708 10002.3 156.916 10012.2160.8035 10018.8162.9542
 10022.1164.7723 10038.6175.165610058.54187.034910081.81199.311410100.99208.5859
#Mann= 3 , 0 , 0
9899.015    0.12       09899.015    0.12       010100.99    0.12       0
#XS Ineff= 2 , 0
       0                               0
Bank Sta=9899.015,10100.99
Exp/Cntr=0.3,0.1

Type RM Length L Ch R = 1 ,1960.379,96.828600,96.828600,96.828600
XS GIS Cut Line= 6
1226609.43875615839705.7741389981226596.97813038839771.096577521
1226592.49642862839804.2841044741226592.28146499839806.272518576
  1226588.397425839836.4695407991226577.08097259839905.093354322
#Sta/Elev= 30
9899.011191.39949900.154191.08489906.834191.38839913.514191.36279916.854191.0642
9920.194190.16499923.534188.71469926.874186.84549933.554182.41229943.574175.0334
9946.914173.03569950.254171.36049966.941163.22539976.873159.03069990.115152.8357
9993.426151.47139996.736150.421110000.04150.289310003.35151.280110016.58158.1554
 10026.5162.541610029.81164.252710033.13166.374510039.78 171.143 10056.4180.3432
10076.36192.483410083.01197.325410086.33199.389510092.98203.0591   10101206.9127
#Mann= 3 , 0 , 0
9899.011    0.12       09899.011    0.12       0   10101    0.12       0
#XS Ineff= 2 , 0
       0                               0
Bank Sta=9899.011,10101
Exp/Cntr=0.3,0.1

Type RM Length L Ch R = 1 , 1863.55,96.828500,96.828500,96.828500
XS GIS Cut Line= 6
 1226516.4240095839693.8090999441226501.60377432839755.172431211
1226496.63306229839791.6701853121226496.41219929839793.657952788
1226491.33313074839833.8609300761226480.50112857839892.332597146
#Sta/Elev= 30
9899.038183.71159909.126183.67449912.502183.33079915.877182.41129932.753173.5942
9949.628164.54889956.379 160.8119959.754158.80879966.422154.51699969.733152.6023
9973.044150.93119976.355149.42059979.666148.04429982.977146.85279986.289145.8459
9999.531  142.9810002.84142.972510009.45146.537810012.76148.128410025.98153.8206
 10032.6156.8404 10035.9158.468510042.53162.465610045.86164.215310055.87169.0732
10059.87171.222110075.89180.298710079.23  181.9310082.57183.377610100.99193.3978
#Mann= 3 , 0 , 0
9899.038    0.12       09899.038    0.12       010100.99    0.12       0
#XS Ineff= 2 , 0
       0                               0
Bank Sta=9899.038,10100.99
Exp/Cntr=0.3,0.1

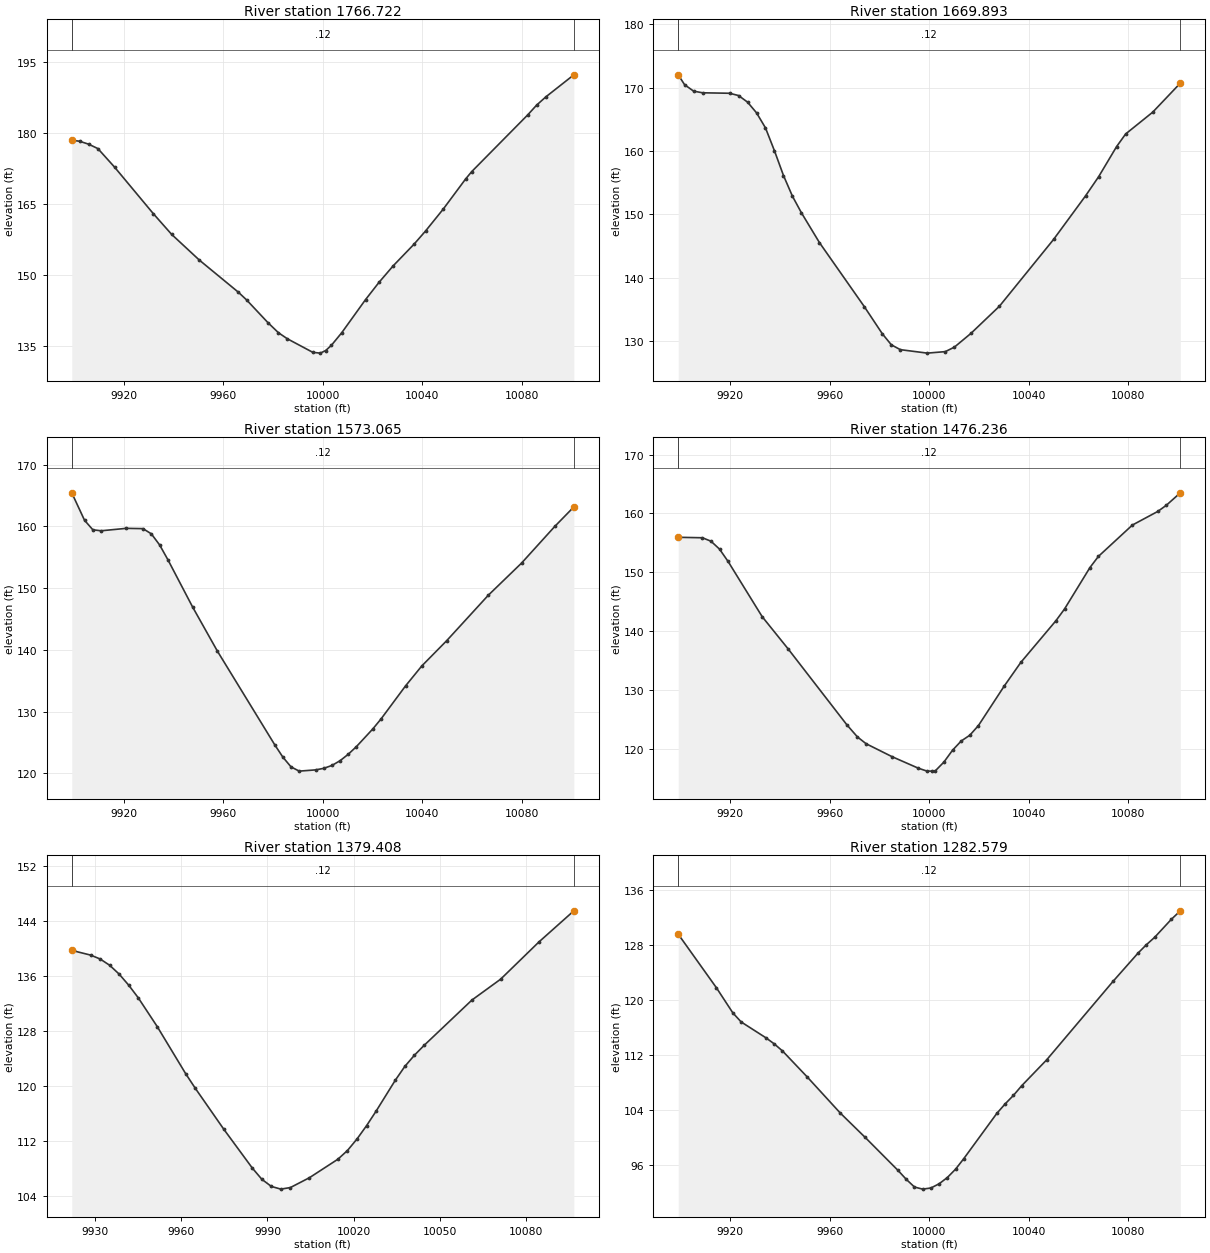
Type RM Length L Ch R = 1 ,1766.722,96.828500,96.828500,96.828500
XS GIS Cut Line= 6
1226459.92480525839677.9222533771226434.08269685839726.910633086
1226420.62996404 839746.511243811226381.37375296839795.921480593
1226365.46611528839822.6762302411226352.86860627839848.241697637
#Sta/Elev= 30
9899.048 178.4249902.179178.19949905.841177.5783 9909.55 176.6499916.242 172.747
9931.806162.94199939.225158.54119950.353 153.1239965.973146.38019969.326144.7364
9977.911139.93819982.159137.80069985.734136.52619995.988133.6605    9999133.4965
10001.13134.034710003.43135.132110007.58137.778210017.21144.805710022.57148.4084
10028.32151.926310036.62156.442310041.32159.263510048.44163.892110057.39170.2111
10059.89171.795310082.36 183.73410086.02185.837810089.68187.554610100.95192.2104
#Mann= 3 , 0 , 0
9899.048    0.12       09899.048    0.12       010100.95    0.12       0
#XS Ineff= 2 , 0
       0                               0
Bank Sta=9899.048,10100.95
Exp/Cntr=0.3,0.1

Type RM Length L Ch R = 1 ,1669.893,96.828500,96.828500,96.828500
XS GIS Cut Line= 4
1226373.52848859839612.7133225751226331.47679554839703.430545259
1226330.66451867 839705.258168381226287.98295936839795.670285463
#Sta/Elev= 30
 9899.01172.01799901.567170.45489905.184169.4453  9908.8169.18019919.648169.1069
9923.264168.74889926.881  167.719930.497166.02159934.113163.63299937.729160.0106
9941.345156.11779944.962152.83779948.578150.2199 9955.81145.52439973.891135.3905
9981.123131.11369984.739129.37569988.356128.61199999.203128.064210006.44128.3014
10010.07129.002810016.73131.172410028.21135.470510049.98146.011210062.84152.8907
10068.12155.924610075.37160.6965   10079162.682310089.88166.120110100.98170.7032
#Mann= 3 , 0 , 0
 9899.01    0.12       0 9899.01    0.12       010100.98    0.12       0
#XS Ineff= 2 , 0
       0                               0
Bank Sta=9899.01,10100.98
Exp/Cntr=0.3,0.1

Type RM Length L Ch R = 1 ,1573.065,96.828500,96.828500,96.828500
XS GIS Cut Line= 6
1226251.50396494839577.2167457171226239.51143152839642.577573138
1226238.75566886839663.131870483 1226241.0454009839695.133750841
1226239.62762621839718.4161509241226228.24699431839776.751952833
#Sta/Elev= 30
9899.031165.43419904.157160.99299907.514159.44079910.872159.28419920.945159.6798
 9927.66159.63159931.018158.79189934.373156.98429937.688154.59259947.635146.9274
9957.581139.7917 9980.64124.61679983.923122.60669987.208121.02669990.498120.3392
9997.078120.540210000.37120.792110003.66121.259710006.95122.034110010.24123.0794
10013.53124.3231 10020.1127.179810023.39128.787110033.25134.143910039.82137.3942
10049.82141.483410066.54148.841410079.91154.048310093.28159.992110100.94163.1508
#Mann= 3 , 0 , 0
9899.031    0.12       09899.031    0.12       010100.94    0.12       0
#XS Ineff= 2 , 0
       0                               0
Bank Sta=9899.031,10100.94
Exp/Cntr=0.3,0.1

Type RM Length L Ch R = 1 ,1476.236,96.828500,96.828500,96.828500
XS GIS Cut Line= 6
1226177.95761278839566.3469325391226167.39626994839600.742188882
1226145.72994539839660.9644314181226145.16000491839662.881504147
1226127.84952581839713.9622161431226115.30555243839758.266049019
#Sta/Elev= 30
9899.019155.93929908.764155.85879912.196155.27059915.628153.9276 9919.06151.8349
9932.788142.43269943.213136.9572 9966.81124.05529971.107121.97099974.594120.8173
9985.054118.60949995.514116.6695    9999116.1677   10001116.155210002.44116.2088
 10005.9117.704310009.37119.719410012.83121.2733 10016.3122.261810019.76123.9014
10030.15130.628710036.83134.656810050.94141.7408 10054.4143.734410064.64 150.796
10068.05152.695110081.69158.018310091.92160.338410095.33161.376710100.98163.5039
#Mann= 3 , 0 , 0
9899.019    0.12       09899.019    0.12       010100.98    0.12       0
#XS Ineff= 2 , 0
       0                               0
Bank Sta=9899.019,10100.98
Exp/Cntr=0.3,0.1

Type RM Length L Ch R = 1 ,1379.408,96.828500,96.828500,96.828500
XS GIS Cut Line= 5
1226070.09664459 839542.923629551226060.16209208839619.336479579
1226060.01959804839621.3313969831226058.48839906839635.449181078
1226044.46116538839715.572336465
#Sta/Elev= 30
9921.944139.75849928.492139.0751  9931.8138.51179935.109137.60059938.417136.3118
9941.726134.71129945.034 132.8849951.651128.68669961.576121.81839964.885119.7177
 9974.81113.75619984.735108.10669988.044106.47839991.352 105.4399994.661 105.048
9997.969105.278110004.57 106.70310014.47109.391410017.79110.651410021.12112.3307
10024.45114.266610027.78116.389510034.44120.873510037.77122.8918 10041.1124.5156
10044.44 125.93710061.09132.536610071.08135.5726 10084.4140.986110096.54145.5111
#Mann= 3 , 0 , 0
9921.944    0.12       09921.944    0.12       010096.54    0.12       0
#XS Ineff= 2 , 0
       0                               0
Bank Sta=9921.944,10096.54
Exp/Cntr=0.3,0.1

Type RM Length L Ch R = 1 ,1282.579,96.828500,96.828500,96.828500
XS GIS Cut Line= 6
1225948.22610814839524.451974557 1225960.9532706 839600.60821623
1225963.64781268839623.2307728351225963.82888423839625.222559243
1225966.41205216839645.8520563551225981.51578542839723.597598142
#Sta/Elev= 30
9899.005129.56149914.337121.8059 9920.99118.13689924.316 116.8319934.295114.5255
9937.621 113.6489940.948112.61989950.927108.83529964.232103.59559974.211100.0761
9987.44195.279359990.745 93.99069994.04992.871549997.353 92.569510000.6592.73396
10003.9693.3435910007.2694.2523510010.5795.4615110013.8896.9919710027.16103.5519
 10030.5104.929210033.84106.165710037.19107.577510047.21111.323210073.95 122.726
10083.98126.819310087.32 128.02810090.66129.106210097.35131.710410100.99132.9534
#Mann= 3 , 0 , 0
9899.005    0.12       09899.005    0.12       010100.99    0.12       0
#XS Ineff= 2 , 0
       0                               0
Bank Sta=9899.005,10100.99
Exp/Cntr=0.3,0.1

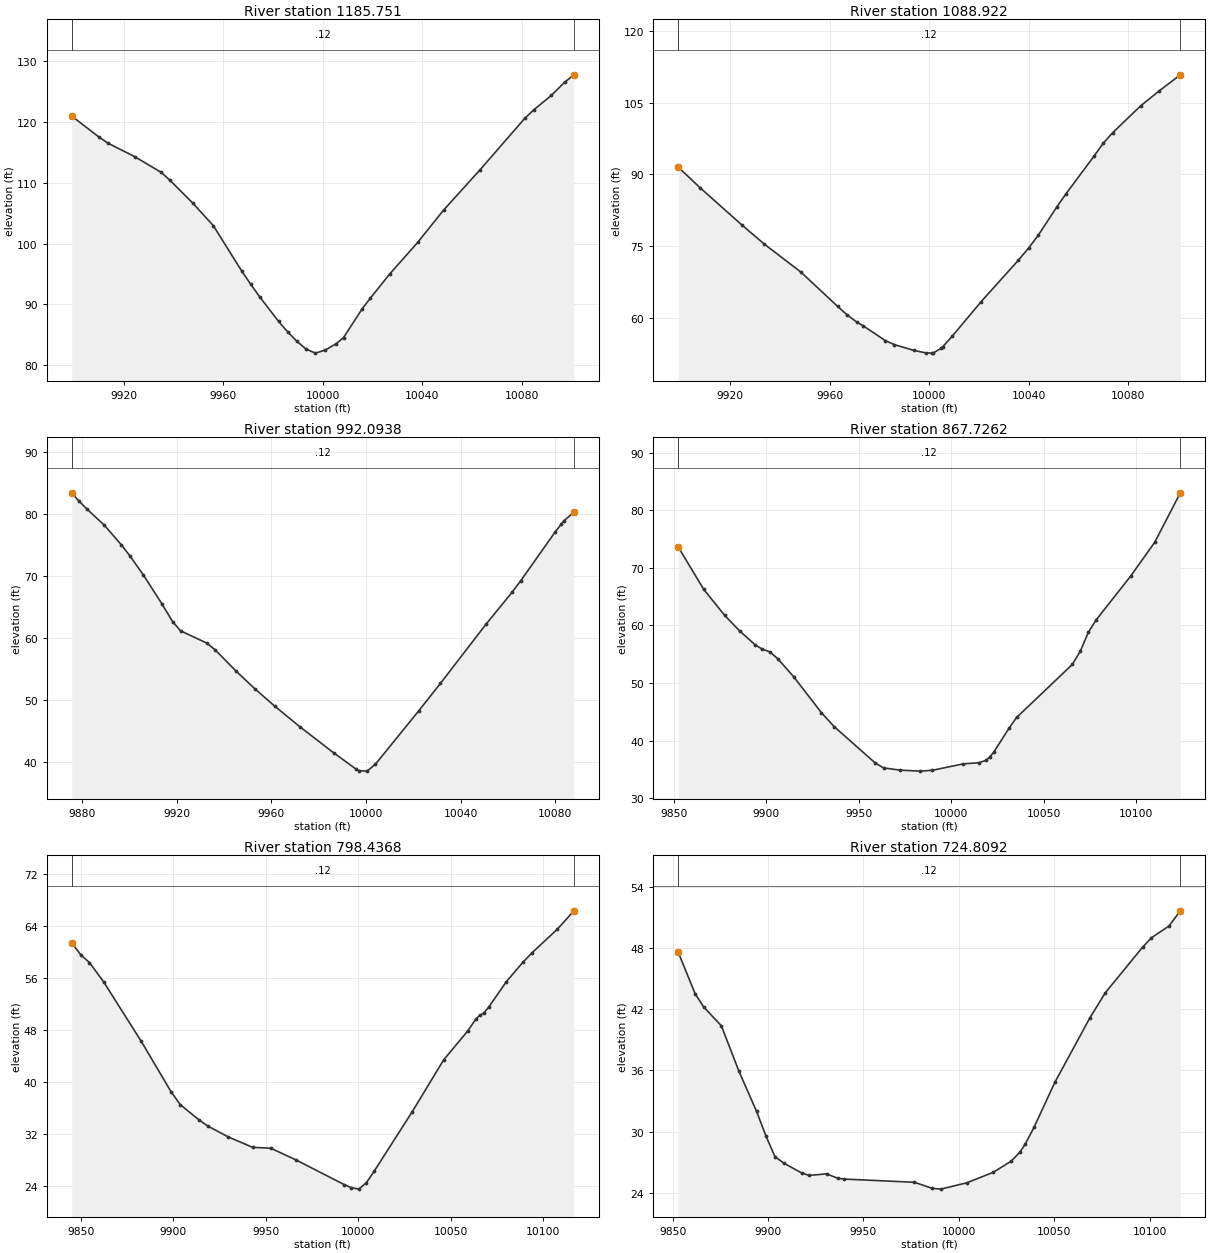
Type RM Length L Ch R = 1 ,1185.751,96.828500,96.828500,96.828500
XS GIS Cut Line= 6
1225832.37044427839568.8576740731225857.27799294839626.982763212
1225874.54143721839659.4012600661225875.59616298839661.100540369
1225891.74604313839690.4260543141225918.63322617839751.232730701
#Sta/Elev= 30
9899.035120.94429910.008117.49149913.577116.49639924.286114.29189934.994111.6986
9938.563110.38019947.626 106.6769955.956102.94389967.318 95.52319970.93993.34265
9974.75291.151279982.18787.209769985.90485.463079989.62183.904439993.33882.61747
9997.05581.97847   1000182.4897810005.4883.5545110008.34 84.539410015.8389.26133
10019.0891.0011410027.0695.0640610038.14100.174410048.56105.490910063.25 112.127
10081.19120.558510084.77121.945910091.95124.361310097.24126.505910100.96127.7298
#Mann= 3 , 0 , 0
9899.035    0.12       09899.035    0.12       010100.96    0.12       0
#XS Ineff= 2 , 0
       0                               0
Bank Sta=9899.035,10100.96
Exp/Cntr=0.3,0.1

Type RM Length L Ch R = 1 ,1088.922,96.828500,96.828500,96.828500
XS GIS Cut Line= 6
1225741.43623018839617.0666957241225770.28963247   839673.235956
 1225789.3765504839704.7380359031225790.47260297839706.410958131
1225809.88579724839737.7181984881225840.26311878839793.082274447
#Sta/Elev= 30
 9899.0291.534059907.79987.208639924.51379.455259933.61875.407979948.37169.53574
9963.16362.331999966.99960.555579970.83559.062589973.28458.318829982.34455.17876
9985.94654.343339993.85253.118999998.60952.60719   10001 52.555110001.5752.56879
10004.7653.5760410005.4353.8944510009.2956.1378210020.8763.3413510035.8972.04451
 10040.174.6594110043.85 77.253410051.33 83.202810055.0785.98896 10066.393.84647
10070.04 96.561610073.7898.7321610085.01104.3526 10092.5107.501110100.99110.8648
#Mann= 3 , 0 , 0
 9899.02    0.12       0 9899.02    0.12       010100.99    0.12       0
#XS Ineff= 2 , 0
       0                               0
Bank Sta=9899.02,10100.99
Exp/Cntr=0.3,0.1

Type RM Length L Ch R = 1 ,992.0938,124.367600,124.367600,124.367600
XS GIS Cut Line= 6
1225655.14309018839638.6683903041225689.74878901 839713.96269014
1225705.03090657839751.4766359931225705.70357942839753.360119797
1225717.17851533839781.5542429041225742.36028466839832.032439043
#Sta/Elev= 30
9875.62783.405459878.50182.141769882.11280.760889889.33378.218639896.55575.04057
9900.16573.263229905.89470.17134 9913.75 65.50269918.21962.669469921.60661.17612
9932.66259.199799936.27358.094419945.17554.641029953.03151.825369961.491 49.0101
9972.119 45.69199986.28941.524959995.929 38.85419996.91738.6455510000.4438.56436
10003.9739.6738710022.2548.2649110031.4452.6957210050.67 62.210410061.67 67.3556
10065.3369.20869   1008077.1172710082.4878.3331610083.6778.9026910087.8580.28168
#Mann= 3 , 0 , 0
9875.627    0.12       09875.627    0.12       010087.85    0.12       0
#XS Ineff= 2 , 0
       0                               0
Bank Sta=9875.627,10087.85
Exp/Cntr=0.3,0.1

Type RM Length L Ch R = 1 ,867.7262,69.289400,69.289400,69.289400
XS GIS Cut Line= 6
 1225498.9254214839699.7918092471225527.56632051839739.230464206
1225561.23072113839777.741740048 1225584.0044348839798.850275713
1225659.15359647839859.5671721751225689.91457963839890.614352526
#Sta/Elev= 30
9852.41873.602729866.19766.237719877.41761.772799885.52759.047539894.11456.58561
9897.69155.899339901.78955.409359906.14754.229619914.86251.051129929.76444.85509
 9936.6542.429669958.91836.093649963.39135.253019972.33834.864949983.22934.69358
9989.76434.8403210006.44 35.958410014.6836.1459110018.7936.5678410020.7337.13562
10022.9137.9848210031.1542.1419110035.2744.0103710065.3653.2076510069.7155.53104
10074.0658.8234610078.4161.0127310096.9468.5669210109.88  74.41310123.7283.00098
#Mann= 3 , 0 , 0
9852.418    0.12       09852.418    0.12       010123.72    0.12       0
#XS Ineff= 2 , 0
       09954.743                       0
Bank Sta=9852.418,10123.72
Exp/Cntr=0.3,0.1

Type RM Length L Ch R = 1 ,798.4368,73.627600,73.627600,73.627600
XS GIS Cut Line= 6
1225445.62681029839745.451531469 1225474.2677094839784.890186429
1225507.93211002 839823.401462271225530.70582369839844.509997936
1225605.85498536839905.2268943971225636.61596852839936.274074748
#Sta/Elev= 30
9845.18261.364089850.24459.492349854.74858.364039862.40855.394519882.68246.27905
9898.82738.518619903.81236.530889913.78234.219969918.767  33.2279929.77631.56573
9942.84929.97752 9952.7829.827129966.20128.054329992.37424.246639996.05823.78854
10000.2123.5463410004.3324.5109510008.5226.2690710029.0435.3863610046.1443.41187
10059.1947.8662210063.5449.6799110065.5350.2269510067.8950.6362910070.5351.53138
10079.9455.3996610089.1758.4734710093.7959.8356810107.65 63.507110116.4966.31127
#Mann= 3 , 0 , 0
9845.182    0.12       09845.182    0.12       010116.49    0.12       0
#XS Ineff= 2 , 0
       09959.781                       0
Bank Sta=9845.182,10116.49
Exp/Cntr=0.3,0.1

Type RM Length L Ch R = 1 ,724.8092,83.648300,83.648300,83.648300
XS GIS Cut Line= 2
 1225395.7302075 839809.141796441225583.44722134839993.603601992
#Sta/Elev= 30
  9852.947.58709 9861.7443.528559866.17342.239599875.53940.364859884.73935.91066
9893.93831.99091 9898.9429.542019903.62127.542599908.302 26.90429917.66425.93442
9921.53725.704189930.73625.855789936.38725.432579939.936 25.34579976.734 25.0298
9985.93324.440189990.53324.3583310004.3324.9887310018.1326.0177110027.3327.08964
10031.9327.9670810034.6928.7423210039.3730.4080510050.3334.8341610068.7341.16942
10076.8143.6283310096.3348.0875110100.9349.0070210110.1350.1570310116.0851.64985
#Mann= 3 , 0 , 0
  9852.9    0.12       0  9852.9    0.12       010116.08    0.12       0
#XS Ineff= 2 , 0
       09967.662                       0
Bank Sta=9852.9,10116.08
Exp/Cntr=0.3,0.1

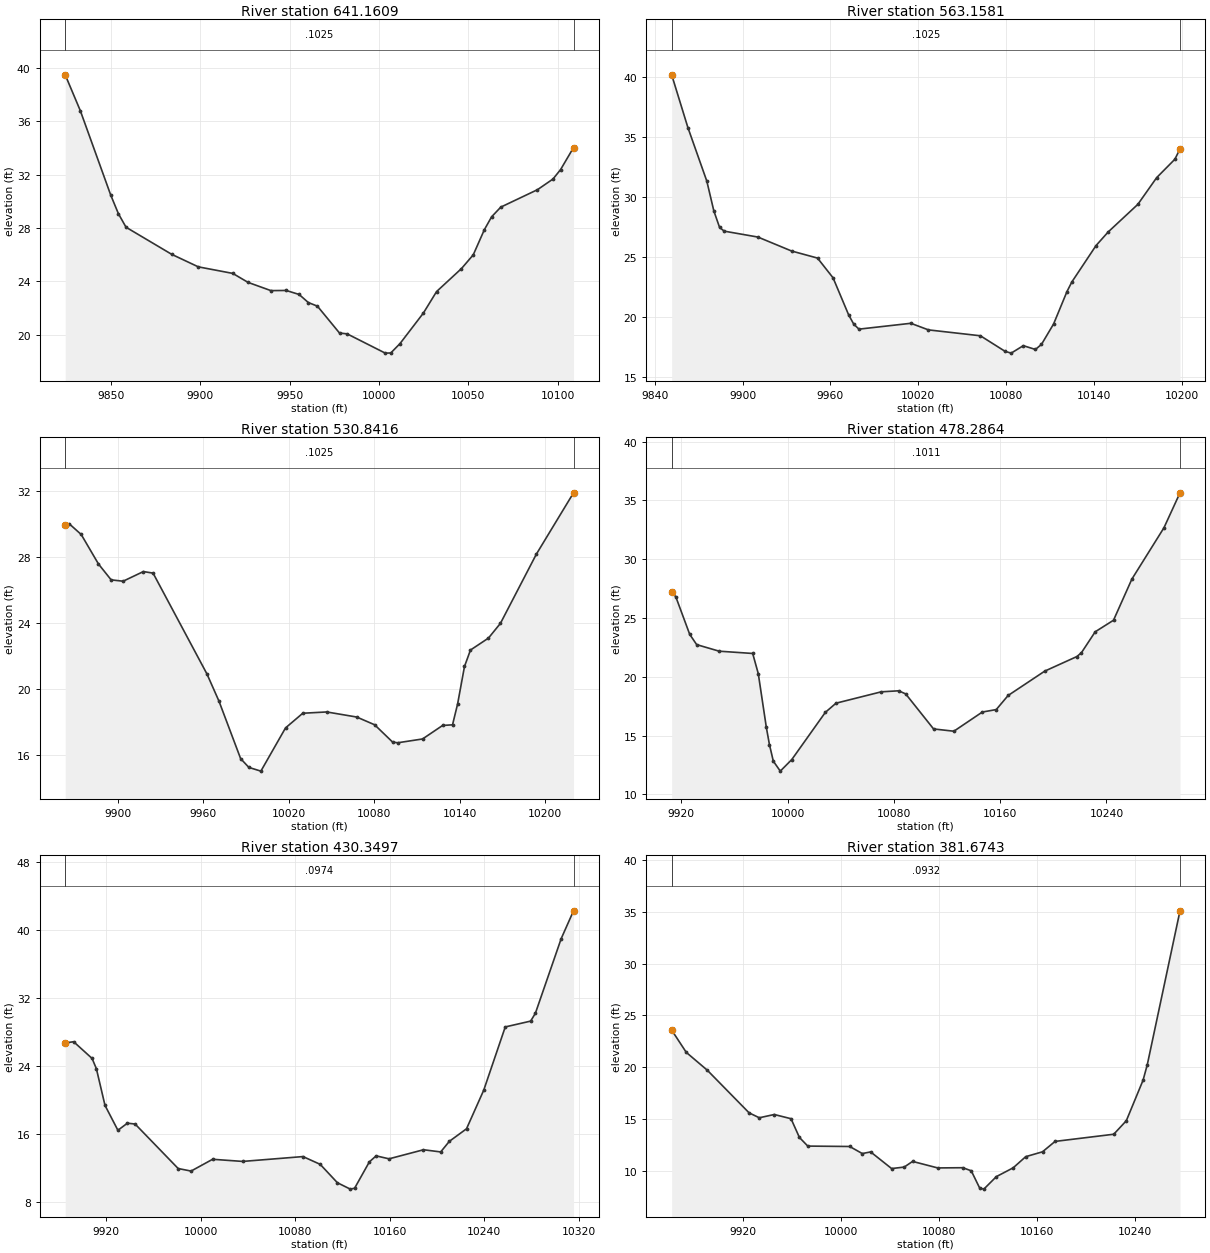
Type RM Length L Ch R = 1 ,641.1609,78.002800,78.002800,78.002800
XS GIS Cut Line= 2
 1225344.5583325839841.4768658731225526.50277692840060.226865888
#Sta/Elev= 30
9824.35239.495939832.80136.806559849.87130.456559854.13829.068969858.405  28.055
 9884.0126.018479898.84425.082519918.14824.589619926.68323.916589939.48523.29821
 9948.0223.309599955.28123.010079960.41122.404939965.54222.129199977.89120.11383
9982.15920.05218 10003.518.6057110006.5918.6179910011.7219.3161910024.8321.61194
10032.2423.2293810046.17 24.954410052.7625.9858710058.9727.8714610063.0228.83845
10068.1529.5648810088.6830.8727410097.3831.6745310101.6432.3847110108.8834.03653
#Mann= 3 , 0 , 0
9824.352  0.1025       09824.352  0.1025       010108.88  0.1025       0
#XS Ineff= 2 , 0
       09943.874        10036.16       0
Bank Sta=9824.352,10108.88
Exp/Cntr=0.3,0.1

Type RM Length L Ch R = 1 ,563.1581,32.316500,32.316500,32.316500
XS GIS Cut Line= 3
1225330.66944361839844.2546436491225396.64166579840006.754643649
1225532.75277692840111.615754768
#Sta/Elev= 30
9851.62340.166189862.71735.762199875.629 31.29939880.42128.81655 9884.3527.43739
9887.50327.127659910.51626.634859933.53525.470239951.23924.881079961.86223.23152
9972.48520.147419976.02619.360229979.56718.9536310014.9819.44157   1002718.89148
 10062.518.3998410079.3717.0999910083.5116.9530410091.7917.5752610100.0817.25833
10104.2217.68471 10112.5 19.388810121.6322.0892410124.9322.8855710141.4925.92788
10149.7827.0611910170.0229.3613510182.9131.5946210195.3333.1271410198.8233.98592
#Mann= 3 , 0 , 0
9851.623  0.1025       09851.623  0.1025       010198.82  0.1025       0
#XS Ineff= 2 , 0
       09971.357        10025.31       0
Bank Sta=9851.623,10198.82
Exp/Cntr=0.3,0.1

Type RM Length L Ch R = 1 ,530.8416,52.555200,52.555200,52.555200
XS GIS Cut Line= 2
1225252.19722137839908.8379769921225530.66944361840131.754643649
#Sta/Elev= 30
9863.20529.945489866.024 29.99699874.429 29.35059886.55827.566469895.44226.60888
9903.84726.526869918.05727.10977 9924.8627.016029962.68320.919969971.088  19.284
9986.30615.806239992.10115.2745610000.51 15.050810017.8117.6620510029.9218.54867
10046.7318.6264710067.7518.3200410080.3517.8513910092.9616.8046110096.55 16.7642
10113.9716.9941810128.0517.8116610134.9917.8486610138.55 19.103610143.39 21.3736
10147.5922.36811 10160.223.0889110168.6123.9799110193.8228.1614910219.9131.86798
#Mann= 3 , 0 , 0
9863.205  0.1025       09863.205  0.1025       010219.91  0.1025       0
#XS Ineff= 2 , 0
       09981.292        10028.51       0
Bank Sta=9863.205,10219.91
Exp/Cntr=0.3,0.1

Type RM Length L Ch R = 1 ,478.2864,47.936700,47.936700,47.936700
XS GIS Cut Line= 3
1225262.61388803839983.8379770071225455.66944361840138.699088097
1225584.14166579840180.365754768
#Sta/Elev= 30
9912.81227.177729915.89526.806549926.38223.605479931.62522.730069948.54422.17194
 9973.78  21.9789977.98620.262799984.05815.689949986.39814.221239989.30112.81932
9994.54511.9696910003.2212.9561210028.4616.9692710036.4917.7484110070.5218.71478
10083.6818.8027410088.9218.53751 10109.915.5584810125.1915.36428 10146.616.99558
10157.0917.20601   1016618.40309 10193.620.4777210217.7421.7143110221.19 22.0431
10231.5423.8206110245.3324.8053410259.1328.3002610283.2732.6659810295.3635.64149
#Mann= 3 , 0 , 0
9912.812  0.1011       09912.812  0.1011       010295.36  0.1011       0
#XS Ineff= 2 , 0
       09963.621        10028.12       0
Bank Sta=9912.812,10295.36
Exp/Cntr=0.3,0.1

Type RM Length L Ch R = 1 ,430.3497,48.675400,48.675400,48.675400
XS GIS Cut Line= 2
1225248.03055468839968.5601992011225434.14166579840356.060199216
#Sta/Elev= 30
9885.528 26.67939892.65726.822429908.25624.857839911.89623.647419919.17519.33952
9930.09416.409919938.12517.245759944.65217.144189981.04911.913399991.96811.61356
10010.1712.9995810035.64 12.7482 10086.613.3180510101.1612.4052310115.7110.24225
10126.639.49039210130.279.59923110142.7312.6934910148.4713.4013410159.3913.05383
10188.5114.1204910203.0713.8639310210.3415.10619 10224.916.5855510239.4621.12486
10257.6628.5620810279.14 29.248110283.1430.1692710304.9738.94817 10315.442.21409
#Mann= 3 , 0 , 0
9885.528  0.0974       09885.528  0.0974       0 10315.4  0.0974       0
#XS Ineff= 2 , 0
       09954.189        10036.82       0
Bank Sta=9885.528,10315.4
Exp/Cntr=0.3,0.1

Type RM Length L Ch R = 1 ,381.6743,69.451200,69.451200,69.451200
XS GIS Cut Line= 2
1225214.00277695 839954.671310321225334.14166579840352.587977007
#Sta/Elev= 30
9861.492 23.59439873.41221.452559890.54719.741729924.81815.628289933.14515.15682
9945.38115.47094 9959.0915.066129965.94413.262689972.79812.4319610007.0712.39258
10017.3511.71317 10024.2 11.869810041.3410.2692510051.6210.4104210058.4810.95624
10079.0410.32956 10099.610.3500410106.4610.0528210113.318.40130610116.748.289439
10127.029.49559710140.73 10.339210151.0111.4133410164.7211.88092   1017512.88184
10222.9813.5721910233.2614.8728210246.9718.7780210250.3920.2568210277.1535.07177
#Mann= 3 , 0 , 0
9861.492  0.0932       09861.492  0.0932       010277.15  0.0932       0
#XS Ineff= 2 , 0
       09969.705        10072.86       0
Bank Sta=9861.492,10277.15
Exp/Cntr=0.3,0.1

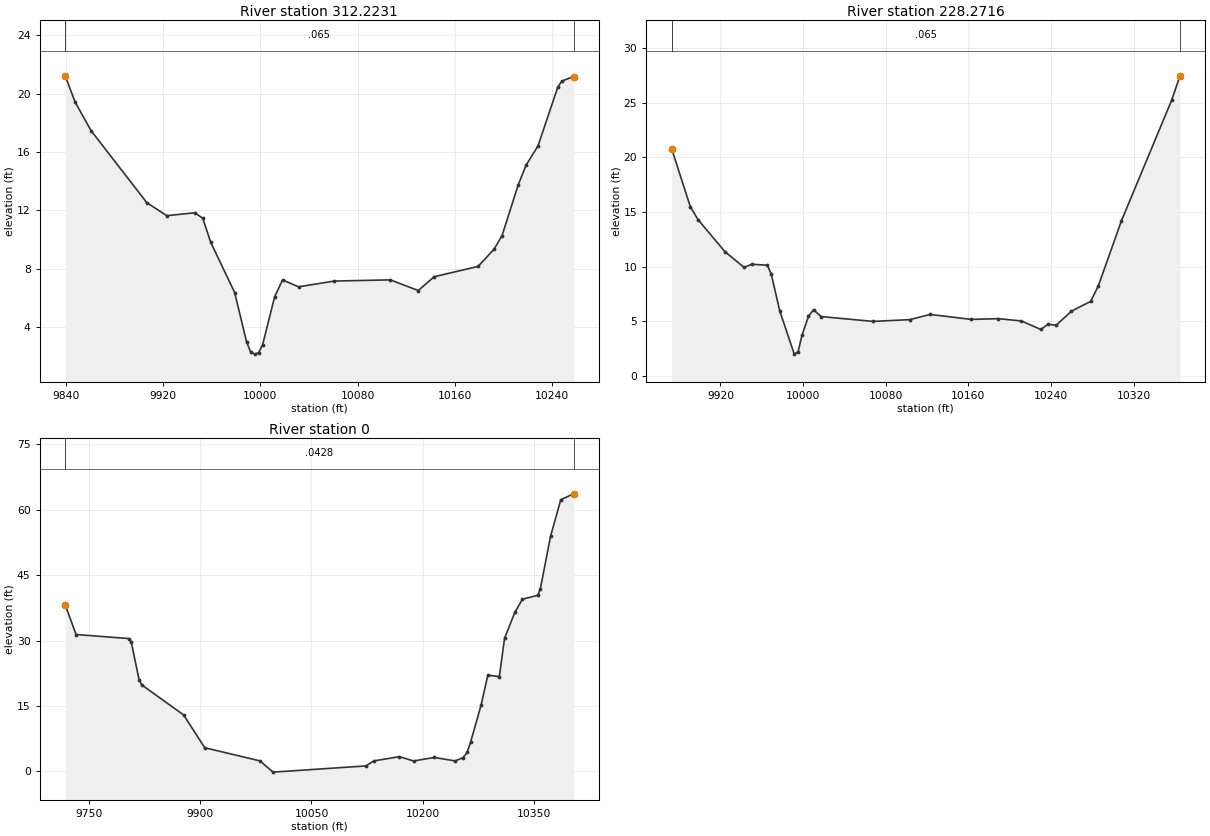
Type RM Length L Ch R = 1 ,312.2231,83.951500,83.951500,83.951500
XS GIS Cut Line= 2
1225205.72839901839961.2793832421225183.46458247840379.186645985
#Sta/Elev= 30
9839.29321.224699847.388 19.4398 9860.5317.470539906.52712.527639922.95411.63892
9945.95311.839499952.52411.465229959.095  9.81119978.807 6.370949988.6642.966691
9991.9492.2940279995.235  2.1486 9998.522.24969310001.81  2.786210011.666.060889
10018.237.23525310031.386.76448410060.947.15782510106.947.23814110129.946.507298
10143.08 7.4549710179.228.16080210192.369.34100110198.9410.2714610212.0813.71203
10218.6515.09099 10228.516.4159410244.9320.4706810248.2220.8633410257.7921.17715
#Mann= 3 , 0 , 0
9839.293   0.065       09839.293   0.065       010257.79   0.065       0
#XS Ineff= 2 , 0
       0 9959.62        10084.17       0
Bank Sta=9839.293,10257.79
Exp/Cntr=0.3,0.1

Type RM Length L Ch R = 1 ,228.2716,228.271600,228.271600,228.271600
XS GIS Cut Line= 2
1225192.47499913839956.7546436491224959.35867971840389.957768649
#Sta/Elev= 30
9872.78620.77219 9890.8315.486519898.28114.302269924.36111.370899942.8929.940553
9950.44110.224399965.34410.13828 9969.079.356995 9977.515.9272979991.4242.014952
9995.1492.2416979998.8753.720367 10005.25.48098210010.056.073728 10017.55.445067
10067.525.00499510103.195.164488 10122.95.64046610162.815.18663410188.895.255448
10211.245.04541810229.874.27800110237.324.74652310244.774.64403510259.675.940816
 10278.36.83377110285.758.26711210308.1114.2077710356.5425.1865210364.7327.43945
#Mann= 3 , 0 , 0
9872.786   0.065       09872.786   0.065       010364.73   0.065       0
#XS Ineff= 2 , 0
       09953.378        10162.61       0
Bank Sta=9872.786,10364.73
Exp/Cntr=0.3,0.1

Type RM Length L Ch R = 1 ,       0,0.000000,0.000000,0.000000
XS GIS Cut Line= 6
1225043.28531119839693.2769194131224958.31760371839903.835086543
1224937.82187246839953.7229246671224864.59139279  840123.1898466
1224819.56407821840242.6781390981224791.66120736840330.253816855
#Sta/Elev= 30
 9718.0138.178589732.69731.401299803.45530.481079806.99329.729379817.60721.01511
9821.14519.853419877.75112.945779906.0545.438328 9980.442.4299159998.174-0.15427
10123.261.26491610133.982.41902410168.613.39481410187.522.40348110215.573.211252
10243.612.41652910254.133.15532810259.784.35312110264.656.82546610278.6715.25025
10287.6922.0775610303.2221.7589510310.2330.5169710324.0236.4586910334.3539.49801
10355.0140.3926710358.4541.8483910372.2353.92226   10386 62.308310403.22 63.6625
#Mann= 3 , 0 , 0
 9718.01  0.0428       0 9718.01  0.0428       010403.22  0.0428       0
#XS Ineff= 2 , 0
       0                               0
Bank Sta=9718.01,10403.22
Exp/Cntr=0.3,0.1